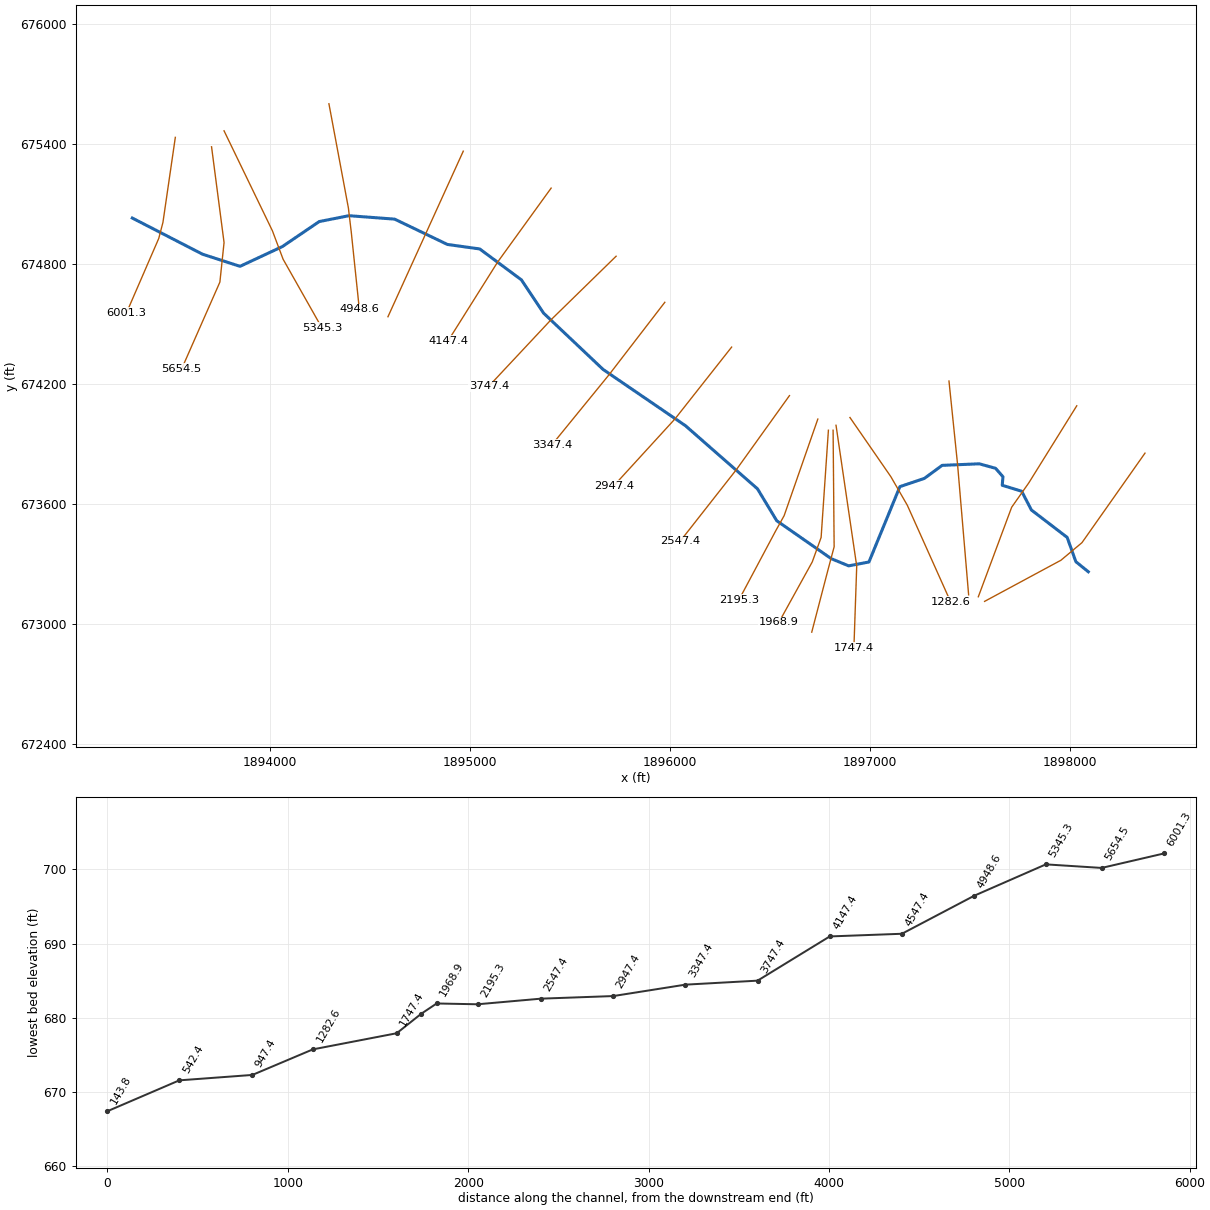
--- RFTrplttRn.prj (project) ---

Proj Title=RFTrplttRn
Current Plan=p01
Default Exp/Contr=0,0
English Units
Geom File=g01
Flow File=f01
Plan File=p01
BEGIN DESCRIPTION:
AMEC Environment & Infrastructure, 2013
Projection: NAD 1983 State Plane West Virginia South FIPS 4702 (US Feet)
Vertical Datum: NAVD 1988
END DESCRIPTION:
DSS Export Rating Curves= 0
DSS Export Rating Curve Sorted= 0
DSS Export Volume Flow Curves= 0
DXF OffsetX= 0
DXF OffsetY= 0
DXF ScaleX= 0
DXF ScaleY= 0

--- RFTrplttRn.p01 (plan) ---

Plan Title=Floodplain
Program Version=4.00
Geom File=g01
Flow File=f01
K Sum by GR=0
Std Step Tol=0.01
Critical Tol=0.01
Num of Std Step Trials=20
Max Error Tol=0.3
Flow Tol Ratio=0.001
Split Flow NTrial=30
Split Flow Tol=0.02
Split Flow Ratio=0.02
Log Output Level=0
Friction Slope Method=1
Unsteady Friction Slope Method=2
Unsteady Bridges Friction Slope Method=1
Global Log Level=0
CheckData=False
Run HTab=0
Run UNet=0
Run PostProcess=0
UNET Theta=0
UNET Theta Warmup=0
UNET ZTol=0
UNET ZSATol=0
UNET MxIter=0
UNET MaxInSteps=0
UNET DtIC=0
UNET DtMin=0
UNET MaxCRTS=0
UNET WFStab=0
UNET SFStab=0
UNET WFX=0
UNET SFX=0
UNET DSS MLevel=0
UNET DZMax Abort=0
UNET Convert EG Bridges=0
UNET Use Existing IB Tables=0
UNET Froude Limit=0
UNET Froude Power=0
Write IC File=0
Echo Input=False
Echo Output=False
Write Detailed=0

--- RFTrplttRn.f01 (steady flow) ---

Flow Title=NFF Regression Equation
Program Version=4.10
Number of Profiles= 1
Profile Names=P100yr
River Rch & RM=RFTrplttRn,Main            ,6001.3
947.6503
River Rch & RM=RFTrplttRn,Main            ,4948.6
993.5687
River Rch & RM=RFTrplttRn,Main            ,2947.4
1055.084
River Rch & RM=RFTrplttRn,Main            ,143.8
 1104.15
Boundary for River Rch & Prof#=RFTrplttRn,Main            , 1
Up Type= 0
Dn Type= 3
Dn Slope=0.01044
DSS Import GetInterval= 0
DSS Import GetPeak= 0
DSS Import FillOption= 0

--- RFTrplttRn.g01 (geometry) ---

Geom Title=USGS 3m DEM
Program Version=4.10

River Reach=RFTrplttRn      ,Main
Reach XY= 30
     1893310.298       675029.26     1893661.082      674848.506
     1893848.657      674787.727      1894060.54      674886.732
     1894244.634      675011.788     1894393.166      675041.093
     1894621.516      675023.961     1894885.513      674897.187
     1895047.088      674874.758     1895255.454       674720.05
     1895366.615      674553.324     1895663.617      674271.977
     1896075.246      673990.634     1896435.704      673674.484
     1896532.039      673514.774     1896804.814      673324.866
     1896891.562      673289.007     1896993.022      673308.397
     1897147.694      673685.381     1897270.164      673726.691
     1897359.017      673791.908     1897544.573      673799.647
     1897626.202      673777.072     1897662.916      673734.912
     1897659.334      673692.249     1897756.466      673662.449
     1897805.099      673568.665     1897983.994      673431.466
     1898027.418      673309.893     1898089.693      673259.552

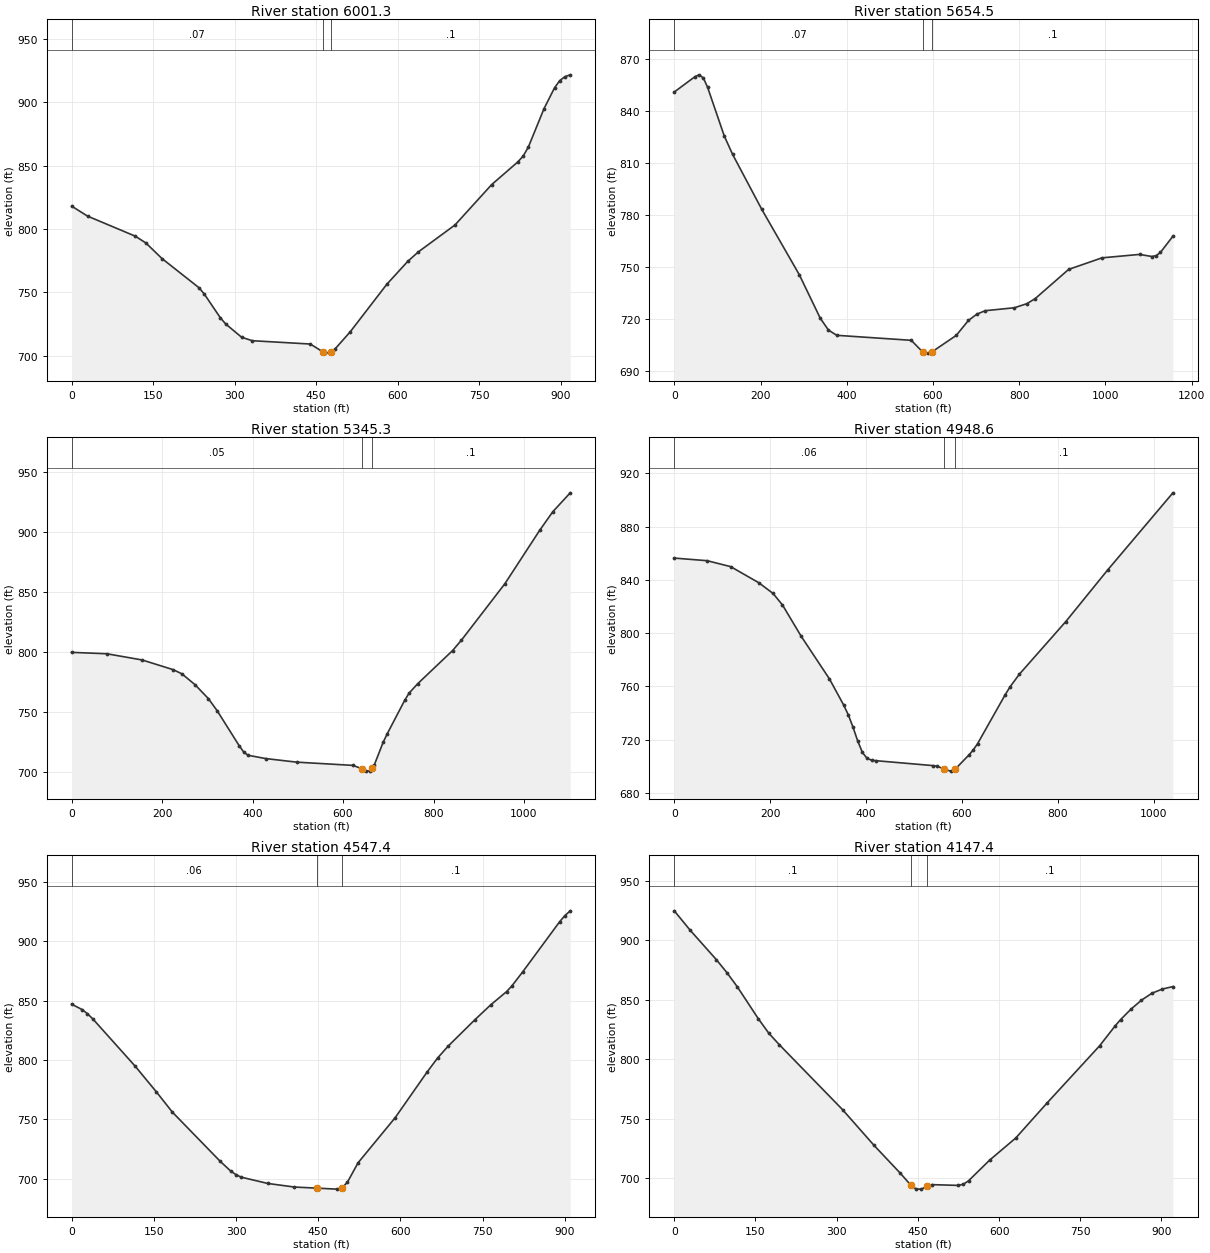
Type RM Length L Ch R = 1 ,6001.3  ,342.5,346.8,349.6
XS GIS Cut Line= 4
     1893525.221      675433.109     1893463.268      675007.462
     1893442.435      674927.601     1893281.537      674556.084
#Sta/Elev= 30
       0  818.08    29.3  810.18   117.3  794.34   136.9  788.94   166.2  776.76
   234.6  753.66   244.4  748.61   273.7  730.04   283.5  725.16   312.8   714.7
   332.4  711.96   439.3  709.34   462.2   703.2   466.8  702.17   477.2  703.07
   485.2  705.68   512.7  718.98   580.1   756.5   618.7  774.57     638  781.96
   705.5  803.21   772.9     835   821.1   852.9   830.8  857.46   840.4  864.56
   869.3  894.91   888.6  911.29   898.2  916.99   907.9  920.12   917.5  921.54
#Mann= 3 , 0 , 0
       0     .07       0   462.2    .045       0   477.2      .1       0
Bank Sta=462.2,477.2
XS Rating Curve= 0 ,0
Exp/Cntr=0.3,0.1

Type RM Length L Ch R = 1 ,5654.5  ,299.4,309.3,320.1
XS GIS Cut Line= 4
     1893706.324      675385.934     1893768.824      674906.767
      1893747.99      674708.851     1893557.018      674274.823
#Sta/Elev= 30
       0  851.04    48.3  859.96      58  860.96    67.6  859.08    77.3  853.72
     116  825.58   135.3  814.99     203  783.21   289.9  745.53   338.3  720.49
   357.6   713.5   376.9   710.5   549.6  707.61   576.7   700.7   587.5  700.21
     597  700.83   653.8  710.43   682.2  719.09   701.6   722.7   720.9  724.71
   788.7  726.41   817.7  728.77   837.1  731.72   914.5  748.56   991.9  755.25
    1079  757.23    1108  756.01  1117.7  756.55  1127.4  758.37  1156.4  767.75
#Mann= 3 , 0 , 0
       0     .07       0   576.7    .045       0     597      .1       0
Bank Sta=576.7,597
XS Rating Curve= 0 ,0
Exp/Cntr=0.3,0.1

Type RM Length L Ch R = 1 ,5345.3  ,402,396.6,391.2
XS GIS Cut Line= 4
     1893768.824      675465.795      1894010.67      674965.372
     1894063.963      674823.434     1894258.196      674479.712
#Sta/Elev= 30
       0   799.6      78  798.42     156  793.25   224.3  785.21   243.8  781.73
     273  772.62   302.3   761.1   321.8  750.98   370.5  721.82   380.3  716.69
     390   713.9     429  711.15   497.3  708.18   622.1  705.47   642.1   702.6
   650.6  700.69     660  700.76   664.1 703.108   669.5   706.2   688.5  724.58
   697.9  731.94   736.3  759.65   745.9  765.62   765.2  773.54   842.2  801.11
   861.5  809.66   957.8  856.79  1034.8  901.29  1063.7  916.72  1102.2  932.44
#Mann= 3 , 0 , 0
       0     .05       0   642.1    .045       0   664.1      .1       0
Bank Sta=642.1,664.1
XS Rating Curve= 0 ,0
Exp/Cntr=0.3,0.1

Type RM Length L Ch R = 1 ,4948.6  ,413.3,401.2,388.6
XS GIS Cut Line= 4
     1894293.129      675601.212     1894390.352      675080.378
     1894404.793      674959.271     1894445.205      674572.635
#Sta/Elev= 30
       0  856.42    68.7  854.44   117.7  849.99   176.6  837.85     206   829.9
   225.7  821.26   264.9  797.66   323.8  765.68   353.2  746.26     363  738.84
   372.8   729.6   382.6  719.24   392.5  710.54   402.3  706.02   412.1  704.66
   421.9  704.27   539.2  700.63   548.6  700.14     562  698.19   576.7  696.46
   586.1  697.93   614.3  708.39   623.6  712.23     633  717.14   690.7  753.94
   700.4   759.6   719.8  769.11     817  808.77   904.5  847.56  1040.5  905.41
#Mann= 3 , 0 , 0
       0     .06       0     562    .045       0   586.1      .1       0
Bank Sta=562,586.1
XS Rating Curve= 0 ,0
Exp/Cntr=0.3,0.1

Type RM Length L Ch R = 1 ,4547.4  ,404,400,396.5
XS GIS Cut Line= 3
     1894964.778       675363.95     1894776.514      674949.726
     1894588.251      674535.501
#Sta/Elev= 30
       0  847.03    19.4  842.42      29  838.96    38.7  834.62   116.2  794.72
   154.9  773.08   183.9  756.14   271.1  714.78   290.4  706.53   300.1  703.46
   309.8  701.35   358.2  696.08   406.6  693.08   447.5  692.15     484  691.32
   493.7  692.51   503.4  697.19   522.8   713.5   590.5  751.45   648.6  789.77
     668  801.74   687.3  811.75   735.7  833.76   764.8  846.41   793.8  857.54
   803.5  862.38   822.9  873.99   890.6  916.37   900.3  921.57     910  925.58
#Mann= 3 , 0 , 0
       0     .06       0   447.5    .045       0   493.7      .1       0
Bank Sta=447.5,493.7
XS Rating Curve= 0 ,0
Exp/Cntr=0.3,0.1

Type RM Length L Ch R = 1 ,4147.4  ,403.9,400,395.6
XS GIS Cut Line= 3
     1895404.074       675179.17     1895136.629      674809.151
     1894889.451      674415.844
#Sta/Elev= 30
       0  924.76    29.1   908.6    77.7  883.76    97.1  872.91   116.6  860.83
   155.4  834.01   174.8  821.82   194.3  812.16   310.8  757.75   369.1  727.67
   417.7  704.24   437.1  694.22   446.8     691   456.6  690.96   466.2   693.3
   475.9  694.73   524.3   694.1     534  695.07   543.6  697.97   582.4  715.27
   630.8  733.92   688.8  763.43   785.6  811.32   814.6  828.21   824.3  833.32
   843.7  842.19     863   849.7   882.4  855.56   901.7  859.06   921.1  861.12
#Mann= 3 , 0 , 0
       0      .1       0   437.1    .045       0   466.2      .1       0
Bank Sta=437.1,466.2
XS Rating Curve= 0 ,0
Exp/Cntr=0.3,0.1

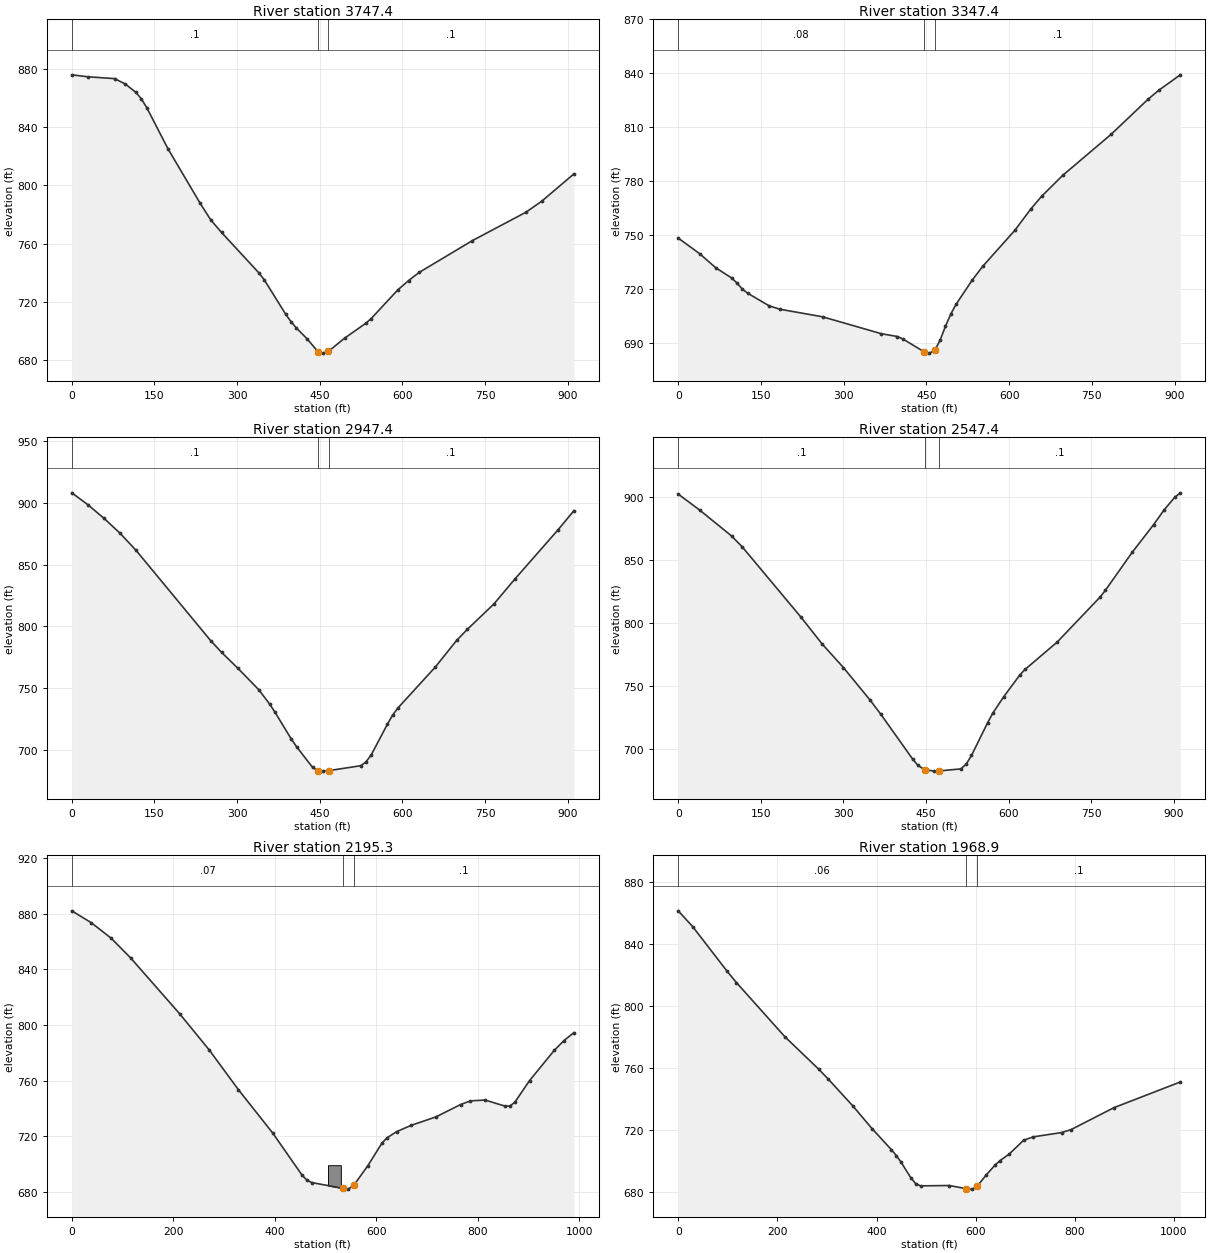
Type RM Length L Ch R = 1 ,3747.4  ,396.7,400,401.5
XS GIS Cut Line= 3
     1895728.962       674838.39     1895402.725      674519.547
     1895092.042      674187.412
#Sta/Elev= 30
       0   875.9    29.1  874.55    77.6   873.3    97.1  869.62   116.5  863.79
   126.2  859.45   135.9  853.48   174.7  825.08   232.9  787.81   252.4  776.28
   271.8  767.74   339.7  739.98   349.4  735.18   388.2  711.66   397.9  706.48
   407.6   702.2     427   694.8   446.5  686.09   456.2  684.99   465.8  686.25
   494.9   695.2   533.6  705.51   543.3  708.72   591.6  728.37     611  734.74
   630.4  740.37   727.1  762.22   823.9   781.6   852.9  789.25     911  807.92
#Mann= 3 , 0 , 0
       0      .1       0   446.5    .045       0   465.8      .1       0
Bank Sta=446.5,465.8
XS Rating Curve= 0 ,0
Exp/Cntr=0.3,0.1

Type RM Length L Ch R = 1 ,3347.4  ,399.8,400,398.2
XS GIS Cut Line= 3
     1895972.387      674607.829     1895694.686      674246.663
     1895407.354         673894.
#Sta/Elev= 30
       0  748.37    38.8  739.71    67.8  731.93    96.9  726.18   106.6   723.4
   116.3     720     126  717.73   164.8  710.74   184.2  708.85   261.7  704.64
   368.4  695.23   397.4  693.68   407.1  692.36   445.9  685.18   455.6  684.45
   465.3  685.99   474.9  691.68   484.6  699.36   494.3   706.2     504  711.66
     533  724.97   552.4  732.76   610.4  752.67   639.5  764.57   658.8  771.54
   697.6  783.31   784.7  805.93   852.4  825.62   871.8  830.58   910.5  839.08
#Mann= 3 , 0 , 0
       0     .08       0   445.9    .045       0   465.3      .1       0
Bank Sta=445.9,465.3
XS Rating Curve= 0 ,0
Exp/Cntr=0.3,0.1

Type RM Length L Ch R = 1 ,2947.4  ,398.9,400,401.6
XS GIS Cut Line= 3
     1896306.439      674383.677     1896023.925      674025.131
     1895717.184      673689.426
#Sta/Elev= 30
       0     908    29.1  898.45    58.3  887.44    87.4  875.42   116.6  861.51
   252.5  788.24   271.9  778.96   301.1  766.26   339.9  748.52   359.4  736.96
   369.1  730.35   398.2  709.01   407.9  702.69     437  685.95   446.8  683.27
   456.5  682.91   466.2   683.3   524.2  687.28   533.9  690.32   543.6  696.16
   572.6  720.66   582.2  728.17   591.9  733.96   659.7  767.06   698.4  788.59
   717.7  797.49   766.1  818.11   804.8  838.59   882.2  877.92   911.2   893.5
#Mann= 3 , 0 , 0
       0      .1       0   446.8    .045       0   466.2      .1       0
Bank Sta=446.8,466.2
XS Rating Curve= 0 ,0
Exp/Cntr=0.3,0.1

Type RM Length L Ch R = 1 ,2547.4  ,349.6,352.2,355.7
XS GIS Cut Line= 3
     1896595.672      674140.954     1896330.875       673771.43
     1896048.897      673411.963
#Sta/Elev= 30
       0  902.32    38.7   889.7    96.7  869.14   116.1   860.5   222.5  804.86
   261.2  783.47   299.8  764.76   348.2  738.97   367.6  727.78   425.6  692.09
   435.3  687.06   447.1  683.78   464.3  682.56     474  682.74   512.9  684.33
   522.6  687.95   532.4     695   561.5  720.83   571.2  728.64   590.7  741.45
   619.9   758.7   629.6  763.23   687.9   784.9   765.7  820.56   775.4  825.95
     824  856.04   862.9  878.01   882.3  889.91   901.8  899.94   911.5  903.32
#Mann= 3 , 0 , 0
       0      .1       0   447.1    .045       0     474      .1       0
Bank Sta=447.1,474
XS Rating Curve= 0 ,0
Exp/Cntr=0.3,0.1

Type RM Length L Ch R = 1 ,2195.3  ,221.8,226.4,229.7
XS GIS Cut Line= 4
     1896737.378      674023.514     1896568.968      673540.158
     1896525.566      673462.033     1896343.296      673119.458
#Sta/Elev= 30
       0  882.26    38.6  873.67    77.3  862.64   115.9  848.38   212.5  808.15
   270.4  782.25   328.4  753.41     396  722.17   453.9  691.82   463.6  688.19
   473.2   686.5  535.34   682.3   545.1   681.8   556.5  684.99   583.4  698.68
   610.9  714.76   620.6  718.58     640   723.2   669.1  727.78   717.6  733.83
   766.1  742.73   785.6  745.37   814.6  745.97   853.5   741.6   863.2  741.67
   872.9  744.32     902  759.97   950.5  781.68   969.9  788.83   989.3  794.46
#Mann= 3 , 0 , 0
       0     .07       0  535.34    .045       0   556.5      .1       0
#Block Obstruct= 1 ,-1
  504.85  530.19  699.05
Bank Sta=535.34,556.5
XS Rating Curve= 0 ,0
Exp/Cntr=0.3,0.1

Type RM Length L Ch R = 1 ,1968.9  ,84.1,85.5,87.6
XS GIS Cut Line= 4
     1896790.323      673967.676     1896753.864      673431.217
     1896709.593      673308.822     1896542.927      673006.738
#Sta/Elev= 30
       0  861.53    29.3  851.28    97.8  822.87   117.3  815.25   215.1  780.27
   283.5  759.29   303.1  752.77     352  735.71     391  720.95   430.2  707.33
   439.9  703.61   449.7  699.22   469.3  689.21     479  685.49   488.8  684.02
     547  684.24  580.06  682.25   584.2  681.91   593.5  681.94   602.8  683.65
   621.4   691.1     640   697.7   649.3  700.35   667.8  704.57   696.6   713.4
   715.8  715.62   773.3  718.42   792.4  720.31   878.7  734.45  1012.9  751.07
#Mann= 3 , 0 , 0
       0     .06       0  580.06    .045       0   602.8      .1       0
Bank Sta=580.06,602.8
XS Rating Curve= 0 ,0
Exp/Cntr=0.3,0.1

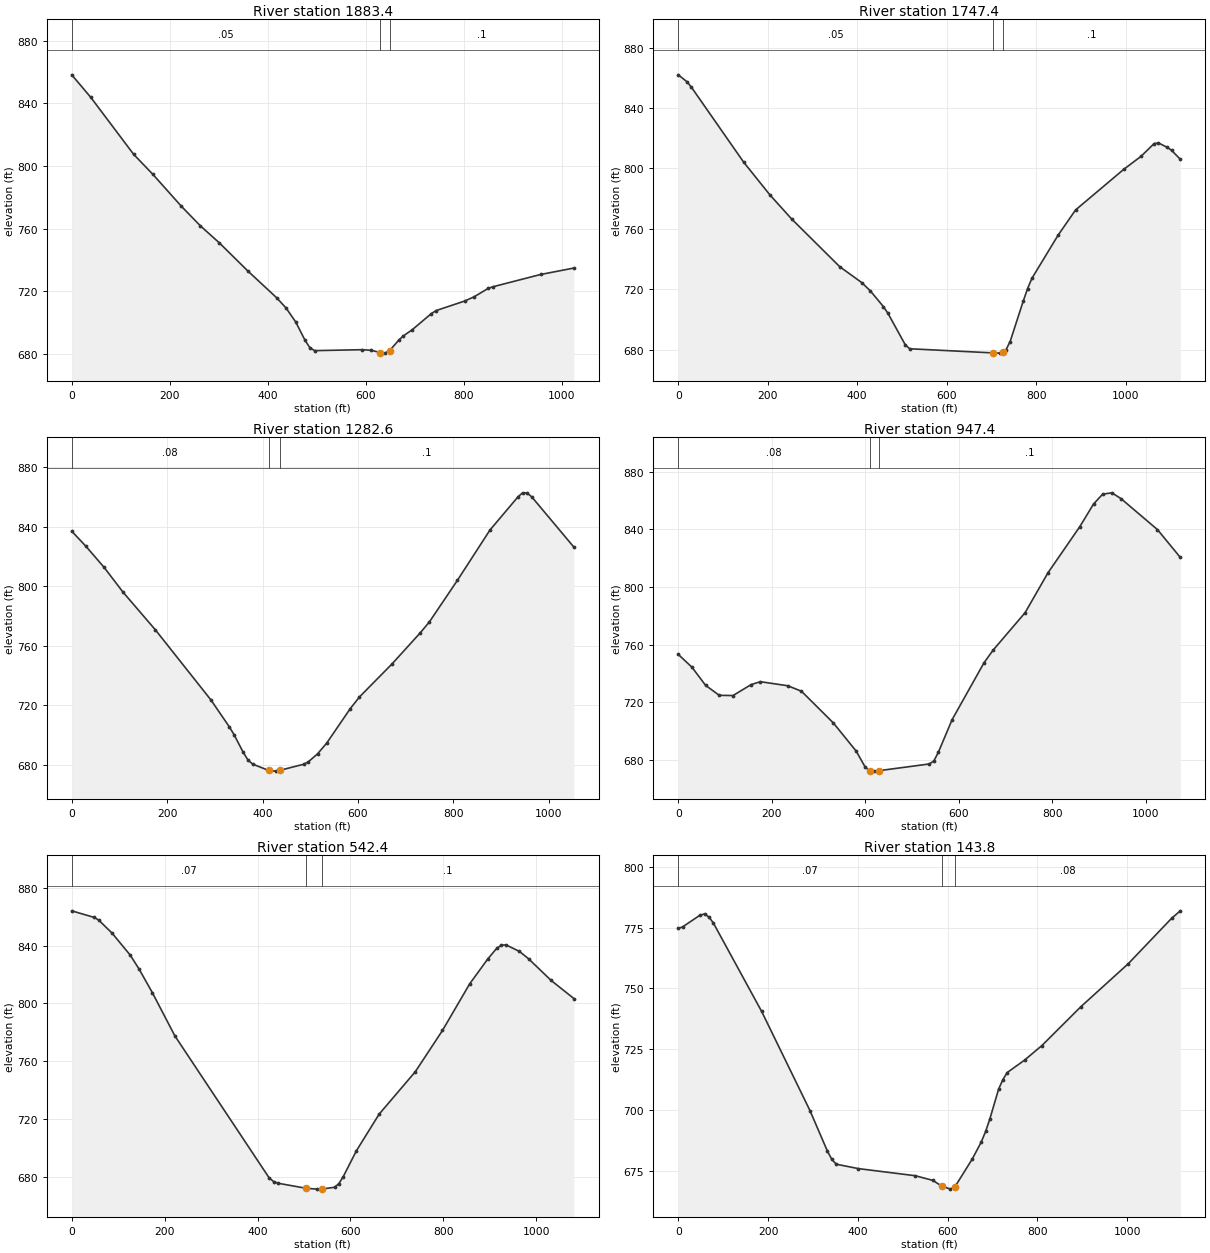
Type RM Length L Ch R = 1 ,1883.4  ,126.8,136,141
XS GIS Cut Line= 4
      1896813.76      673967.676     1896818.968      673384.342
     1896787.718      673267.155     1896706.989      672957.259
#Sta/Elev= 30
       0   858.3    38.9  843.86   126.4  807.48   165.3  794.82   223.6  774.38
   262.5  761.84   301.4  750.91   359.7  732.91   418.1  715.93   437.5  709.32
     457   700.5   476.4  688.61   486.1  683.95   495.8  682.11   592.7  682.71
   611.3  682.33     630  680.88   639.3  680.52   648.7  682.06   667.3  688.75
   676.6  691.45   695.3  695.54   733.8  705.71   743.5  707.68   801.7  713.76
   821.1  716.46   850.2   721.9   859.9  722.93     957  730.75  1024.9  734.87
#Mann= 3 , 0 , 0
       0     .05       0     630    .045       0   648.7      .1       0
Bank Sta=630,648.7
XS Rating Curve= 0 ,0
Exp/Cntr=0.3,0.1

Type RM Length L Ch R = 1 ,1747.4  ,456.3,464.9,475.9
XS GIS Cut Line= 3
     1896828.353      673992.476     1896931.855      673287.619
     1896917.756      672878.288
#Sta/Elev= 30
       0  861.93    19.5  857.37    29.3   853.8   146.4   804.1   204.9  782.52
   253.7  766.52   361.1     735   409.9  724.58   429.4  719.02   458.7  708.59
   468.4  704.35   507.5  683.34   517.2  680.78   702.7  678.05   719.9  677.89
  726.84   678.8   731.9  679.82   741.7  685.55   770.9  712.22   780.7  720.58
   790.4  727.37   848.9  755.89     888   772.6   995.2  799.33  1034.2  808.04
  1063.5  816.47  1073.2  816.89  1092.7  813.98  1102.5     812    1122  806.08
#Mann= 3 , 0 , 0
       0     .05       0   702.7    .045       0  726.84      .1       0
Bank Sta=702.7,726.84
XS Rating Curve= 0 ,0
Exp/Cntr=0.3,0.1

Type RM Length L Ch R = 1 ,1282.6  ,344.3,335.1,325.9
XS GIS Cut Line= 4
     1896898.004      674031.357     1897102.389      673735.471
     1897184.854      673592.242     1897400.567      673110.614
#Sta/Elev= 30
       0  836.98    29.2  827.03      68  812.62   106.9  796.25     175  770.81
   291.6  723.63   330.5   705.4   340.2  700.25   359.6  688.24   369.3  683.26
   379.1  680.43  413.06  676.15   427.7  675.71   437.4  676.35     486  680.31
   495.7  681.87   515.2   687.3   534.7  694.65   583.5  717.57   603.1  725.56
   671.5  747.81   730.1   768.5   749.7  776.01   808.3  803.88   876.7  837.77
   935.3  860.03   945.1   862.8   954.9  862.62   964.7  859.96  1052.6  826.32
#Mann= 3 , 0 , 0
       0     .08       0  413.06    .045       0   437.4      .1       0
Bank Sta=413.06,437.4
XS Rating Curve= 0 ,0
Exp/Cntr=0.3,0.1

Type RM Length L Ch R = 1 ,947.4   ,415.1,405,390.3
XS GIS Cut Line= 3
     1897393.114      674213.815     1897436.122      673796.105
     1897491.365      673144.076
#Sta/Elev= 30
       0  753.32    29.3   744.4    58.6  731.78    87.9  724.86   117.2  724.73
   156.2  732.35   175.8  734.33   234.4  731.51   263.7   727.7     332  705.68
   380.9   686.1   400.4  674.82   410.2   672.5   419.9  672.26   429.7  672.59
   537.1  677.22   546.9  679.29   556.6  685.35     586  707.97   654.3  747.48
   673.8  756.27   742.2  782.24     791  809.84   859.4  842.02   888.7   857.7
   908.2  864.51   927.8  865.42   947.3  861.43  1025.4   839.9  1074.3  820.58
#Mann= 3 , 0 , 0
       0     .08       0   410.2    .045       0   429.7      .1       0
Bank Sta=410.2,429.7
XS Rating Curve= 0 ,0
Exp/Cntr=0.3,0.1

Type RM Length L Ch R = 1 ,542.4   ,405.5,398.6,392.5
XS GIS Cut Line= 4
     1898031.989      674090.072     1897792.406      673704.655
     1897706.468      673582.259     1897539.802      673134.342
#Sta/Elev= 30
       0  864.05    48.3  859.48    57.9  857.67    86.9   848.6   125.5  833.57
   144.8  823.86   173.8  807.29   222.1  777.52   424.8  679.46   434.5   676.8
   444.2  675.61   504.8  672.11   528.6  671.53   537.9  671.56     566  672.82
   575.3  675.38   584.7   680.2   613.1  698.11   661.9  723.38   739.9  752.77
   798.4  781.31     857  813.54     896  830.79   915.5  838.24   925.2  840.22
     935  840.53   964.2  835.96   983.8  830.87  1032.5  815.86  1081.3  803.39
#Mann= 3 , 0 , 0
       0     .07       0   504.8    .045       0   537.9      .1       0
Bank Sta=504.8,537.9
XS Rating Curve= 0 ,0
Exp/Cntr=0.3,0.1

Type RM Length L Ch R = 1 ,143.8   ,137.1,143.8,148.8
XS GIS Cut Line= 4
     1898373.135      673853.092     1898058.031      673405.176
     1897952.888      673317.194     1897571.139      673111.339
#Sta/Elev= 30
       0   774.7     9.8  775.36    48.9  780.21    58.7  780.67    68.5   779.4
    78.2  776.97   185.8  740.54   293.4  699.73   332.5  682.94   342.3  679.57
   352.1  677.63     401  675.82   528.1  672.88   567.2  670.96   586.8  668.63
   606.4  667.36   616.2  668.26   655.4  679.88     675  686.75   684.8  691.11
   694.4   696.4   713.7  708.53   723.3  712.49   732.9  715.37   771.5  720.48
     810  726.46   896.8  742.45  1002.8  760.23  1099.2   778.9  1118.5  781.96
#Mann= 3 , 0 , 0
       0     .07       0   586.8    .045       0   616.2     .08       0
Bank Sta=586.8,616.2
XS Rating Curve= 0 ,0
Exp/Cntr=0.3,0.1

Chan Stop Cuts=-1
Use User Specified Reach Order=0
Composite Channel Slope=5